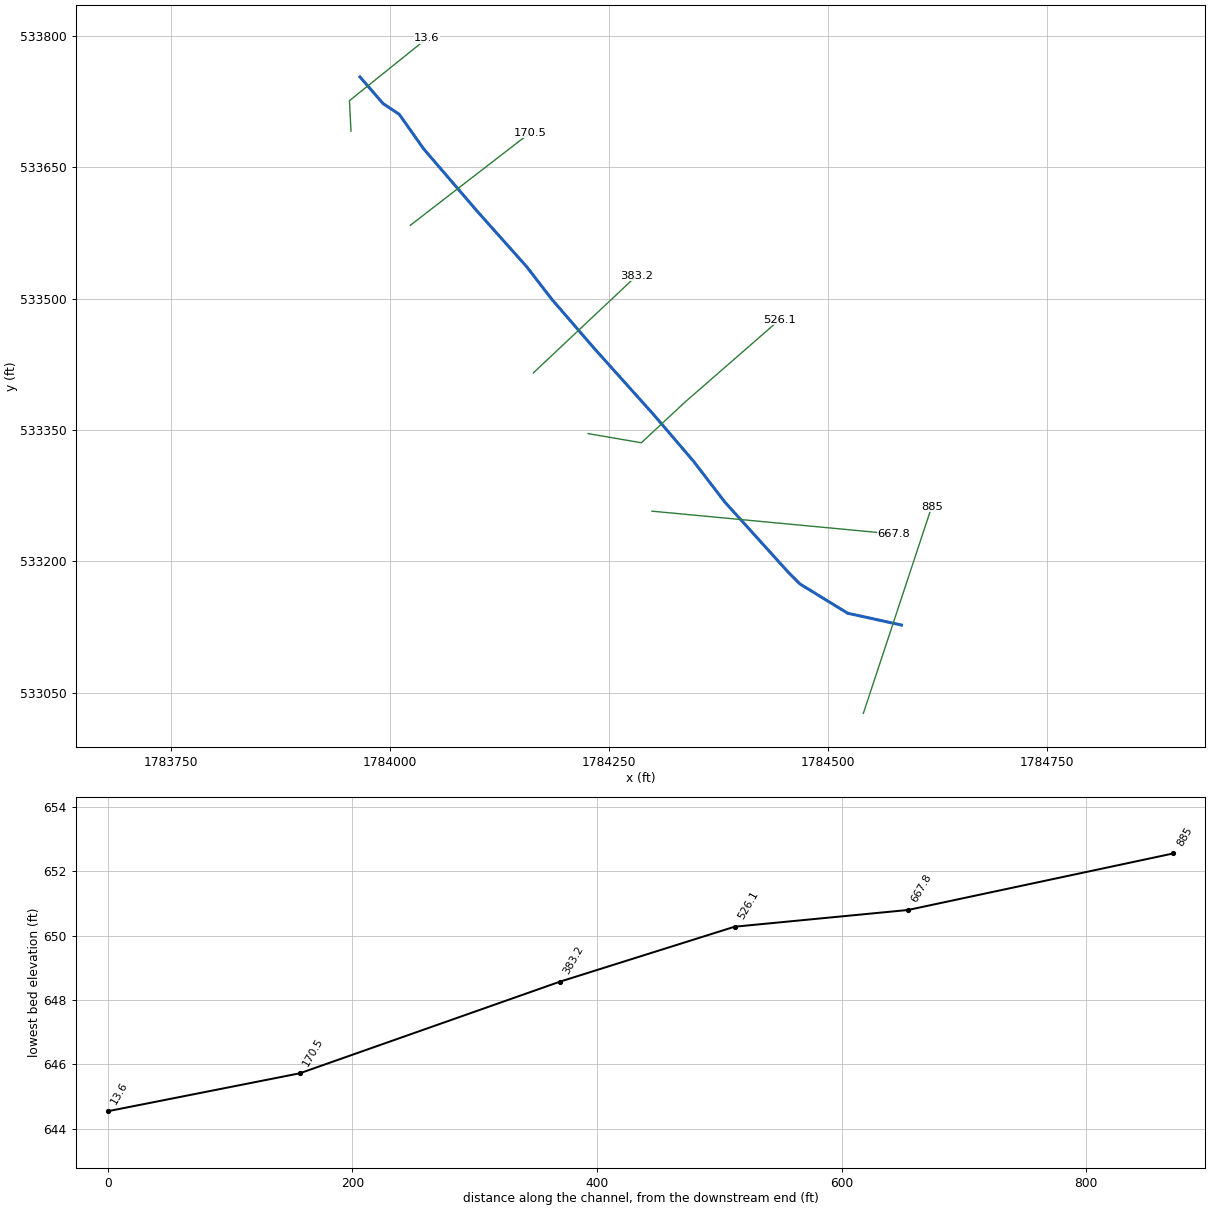
--- UNIONFK.prj (project) ---

Proj Title=UNIONFK
Current Plan=p01
Default Exp/Contr=0,0
English Units
Geom File=g01
Flow File=f01
Plan File=p01
BEGIN DESCRIPTION:
END DESCRIPTION:
DSS Export Rating Curves= 0
DSS Export Rating Curve Sorted= 0
DSS Export Volume Flow Curves= 0
DXF OffsetX= 0
DXF OffsetY= 0
DXF ScaleX= 0
DXF ScaleY= 0

--- UNIONFK.p01 (plan) ---

Plan Title=Floodplain
Program Version=4.00
Geom File=g01
Flow File=f01
K Sum by GR=0
Std Step Tol=0.01
Critical Tol=0.01
Num of Std Step Trials=20
Max Error Tol=0.3
Flow Tol Ratio=0.001
Split Flow NTrial=30
Split Flow Tol=0.02
Split Flow Ratio=0.02
Log Output Level=0
Friction Slope Method=1
Unsteady Friction Slope Method=2
Unsteady Bridges Friction Slope Method=1
Global Log Level=0
CheckData=False
Run HTab=0
Run UNet=0
Run PostProcess=0
UNET Theta=0
UNET Theta Warmup=0
UNET ZTol=0
UNET ZSATol=0
UNET MxIter=0
UNET MaxInSteps=0
UNET DtIC=0
UNET DtMin=0
UNET MaxCRTS=0
UNET WFStab=0
UNET SFStab=0
UNET WFX=0
UNET SFX=0
UNET DSS MLevel=0
UNET DZMax Abort=0
UNET Convert EG Bridges=0
UNET Use Existing IB Tables=0
UNET Froude Limit=0
UNET Froude Power=0
Write IC File=0
Echo Input=False
Echo Output=False
Write Detailed=0

--- UNIONFK.f01 (steady flow) ---

Flow Title=NFF Regression Equation
Program Version=4.10
Number of Profiles= 1
Profile Names=P100yr
River Rch & RM=UNIONFK,Main            ,885
832.1791
River Rch & RM=UNIONFK,Main            ,526.1
1090.743
Boundary for River Rch & Prof#=UNIONFK,Main            , 1
Up Type= 0
Dn Type= 3
Dn Slope=0.008
DSS Import GetInterval= 0
DSS Import GetPeak= 0
DSS Import FillOption= 0

--- UNIONFK.g01 (geometry) ---

Geom Title=USGS 10m DEM
Program Version=4.10

River Reach=UNIONFK         ,Main
Reach XY= 16
     1784583.814      533127.199     1784583.471      533127.274
     1784522.426      533140.676     1784468.083      533174.016
     1784454.548      533187.551     1784382.071      533267.738
     1784346.603         533314.     1784301.113      533367.201
     1784234.033      533441.991     1784184.687      533499.048
     1784156.159      533536.057     1784099.102      533600.053
     1784038.191      533670.988     1784010.434       533710.31
     1783991.929      533722.647     1783965.554      533753.036

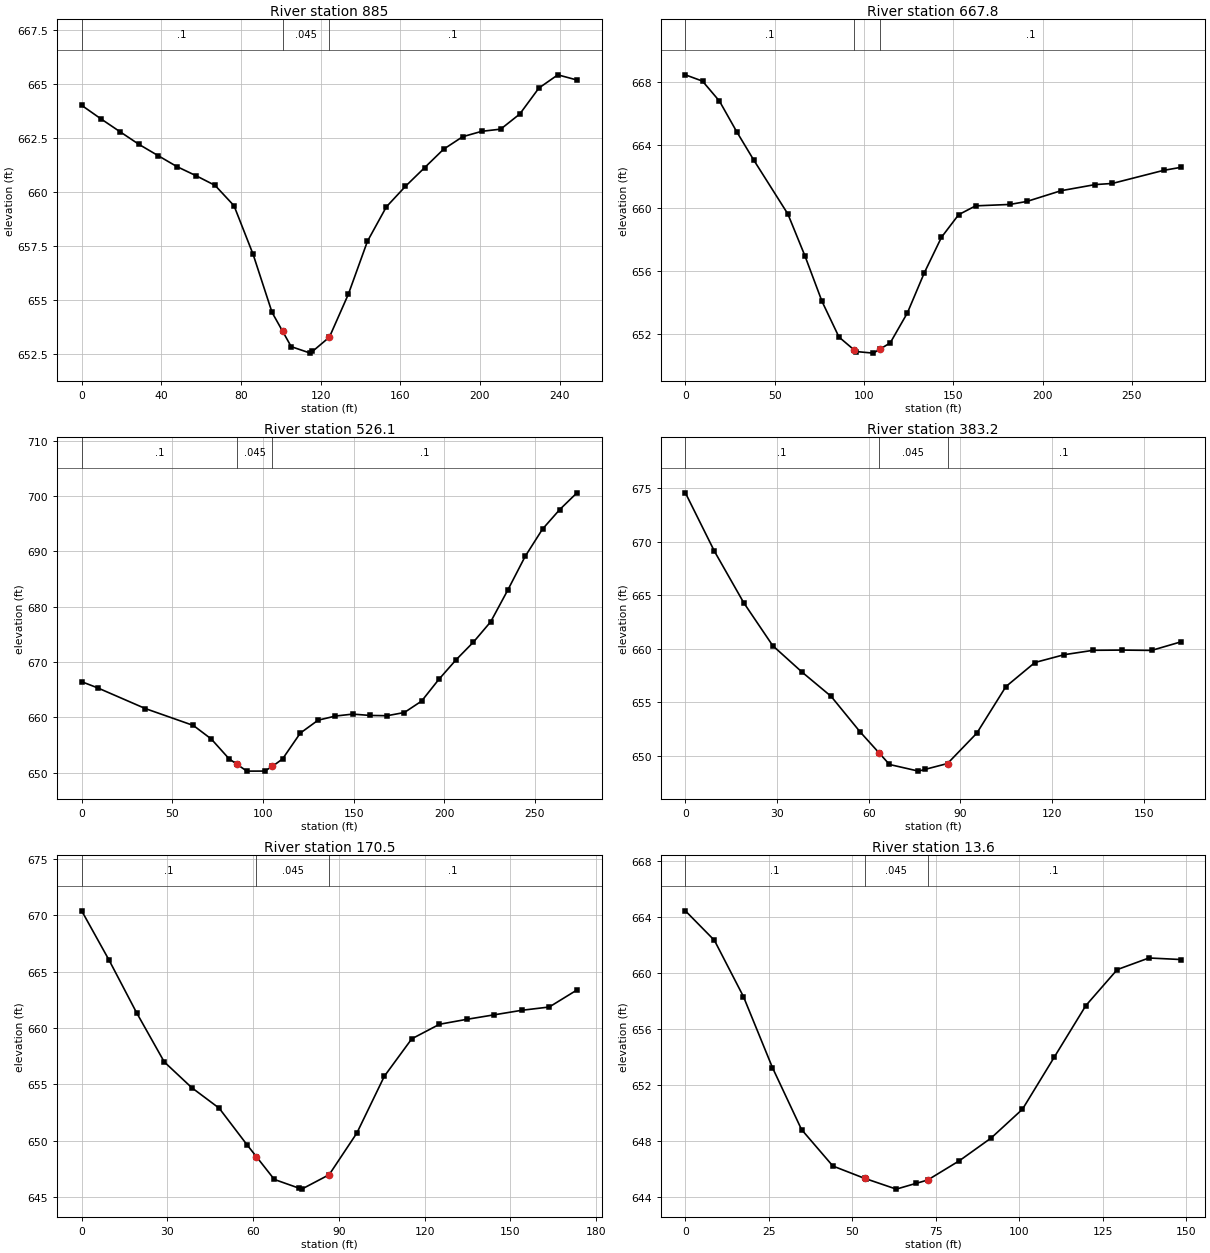
Type RM Length L Ch R = 1 ,885     ,253.4,217.1,180.4
XS GIS Cut Line= 2
     1784540.323      533026.314     1784618.448      533262.425
#Sta/Elev= 29
       0  664.01     9.6  663.39    19.1   662.8    28.7  662.21    38.3  661.69
    47.8  661.18    57.4  660.76      67  660.31    76.5  659.37    86.1  657.12
    95.6  654.44   100.9  653.57   105.2  652.86   114.8  652.56   115.9  652.64
   124.4   653.3   133.9  655.28   143.5  657.73     153  659.32   162.6  660.27
   172.2  661.13   181.7  661.98   191.3  662.56   200.9  662.81   210.4  662.91
     220  663.61   229.6  664.81   239.1  665.42   248.7  665.18
#Mann= 3 , 0 , 0
       0      .1       0   100.9    .045       0   124.4      .1       0
Bank Sta=100.9,124.4
XS Rating Curve= 0 ,0
Exp/Cntr=0.3,0.1

Type RM Length L Ch R = 1 ,667.8   ,116.8,141.7,167
XS GIS Cut Line= 2
     1784299.004      533257.217     1784575.046      533231.175
#Sta/Elev= 26
       0  668.45     9.6  668.05    19.1  666.78    28.7  664.85    38.2  663.06
    57.4  659.62    66.9  656.98    76.5  654.08      86  651.82    94.2  651.03
    95.6   650.9   105.2   650.8   109.2  651.07   114.7  651.45   124.3  653.35
   133.8   655.9   143.4  658.15     153  659.58   162.5  660.14   181.7  660.23
   191.2  660.42   210.3   661.1   229.5  661.49     239  661.56   267.7  662.39
   277.3  662.58
#Mann= 3 , 0 , 0
       0      .1       0    94.2    .045       0   109.2      .1       0
Bank Sta=94.2,109.2
XS Rating Curve= 0 ,0
Exp/Cntr=0.3,0.1

Type RM Length L Ch R = 1 ,526.1   ,142.8,142.9,143
XS GIS Cut Line= 4
     1784226.087      533345.758     1784286.851      533335.342
     1784337.198      533382.217     1784444.837      533475.967
#Sta/Elev= 28
       0  666.43     8.8  665.32    35.2  661.57    61.6  658.53    71.5  656.08
    81.3  652.51    85.7  651.51    91.1  650.28     101  650.29  105.23  651.15
   110.8  652.48   120.6  657.15   130.4  659.48     140  660.23   149.5  660.58
     159  660.34   168.5  660.29     178  660.87   187.5  662.93     197  666.85
   206.6  670.42   216.1  673.59   225.6  677.25   235.1  683.02   244.6  689.05
   254.2     694   263.7  697.53   273.2  700.55
#Mann= 3 , 0 , 0
       0      .1       0    85.7    .045       0  105.23      .1       0
Bank Sta=85.7,105.23
XS Rating Curve= 0 ,0
Exp/Cntr=0.3,0.1

Type RM Length L Ch R = 1 ,383.2   ,214.8,212.7,210.4
XS GIS Cut Line= 2
     1784163.587      533415.203     1784281.643      533526.314
#Sta/Elev= 20
       0  674.55     9.5   669.1    19.1  664.29    28.6  660.28    38.2  657.81
    47.7  655.55    57.2  652.23    63.4  650.27    66.8  649.19    76.3  648.57
    78.4  648.73    85.8  649.28    95.4  652.12   104.9  656.46   114.4  658.71
     124  659.44   133.5  659.85     143  659.87   152.6  659.84   162.1  660.63
#Mann= 3 , 0 , 0
       0      .1       0    63.4    .045       0    85.8      .1       0
Bank Sta=63.4,85.8
XS Rating Curve= 0 ,0
Exp/Cntr=0.3,0.1

Type RM Length L Ch R = 1 ,170.5   ,156.5,157,157.5
XS GIS Cut Line= 2
     1784022.962      533583.606     1784160.115      533689.508
#Sta/Elev= 21
       0   670.4     9.6  666.02    19.2  661.37    28.9     657    38.5  654.72
    48.1   652.9    57.8  649.67    61.1  648.61    67.4  646.58    76.1   645.8
      77  645.72    86.6     647    96.3   650.7   105.9  655.73   115.5  659.05
   125.2  660.34   134.8  660.78   144.4  661.18     154  661.58   163.6  661.87
   173.3  663.38
#Mann= 3 , 0 , 0
       0      .1       0    61.1    .045       0    86.6      .1       0
Bank Sta=61.1,86.6
XS Rating Curve= 0 ,0
Exp/Cntr=0.3,0.1

Type RM Length L Ch R = 1 ,13.6    ,12.7,13.6,14.4
XS GIS Cut Line= 3
     1783955.254      533691.245     1783953.518      533725.967
      1784042.06      533797.147
#Sta/Elev= 19
       0  664.43     8.7  662.32    17.4   658.3    26.1  653.22    34.8   648.8
    44.2  646.19    53.7  645.31    54.1  645.28    63.2  644.54    69.1  644.95
    72.6  645.19    82.1  646.57    91.6  648.19     101  650.25   110.5  653.96
     120  657.66   129.4  660.23   138.9  661.06   148.4  660.95
#Mann= 3 , 0 , 0
       0      .1       0    53.7    .045       0    72.6      .1       0
Bank Sta=53.7,72.6
XS Rating Curve= 0 ,0
Exp/Cntr=0.3,0.1

Chan Stop Cuts=-1
Use User Specified Reach Order=0
Composite Channel Slope=5